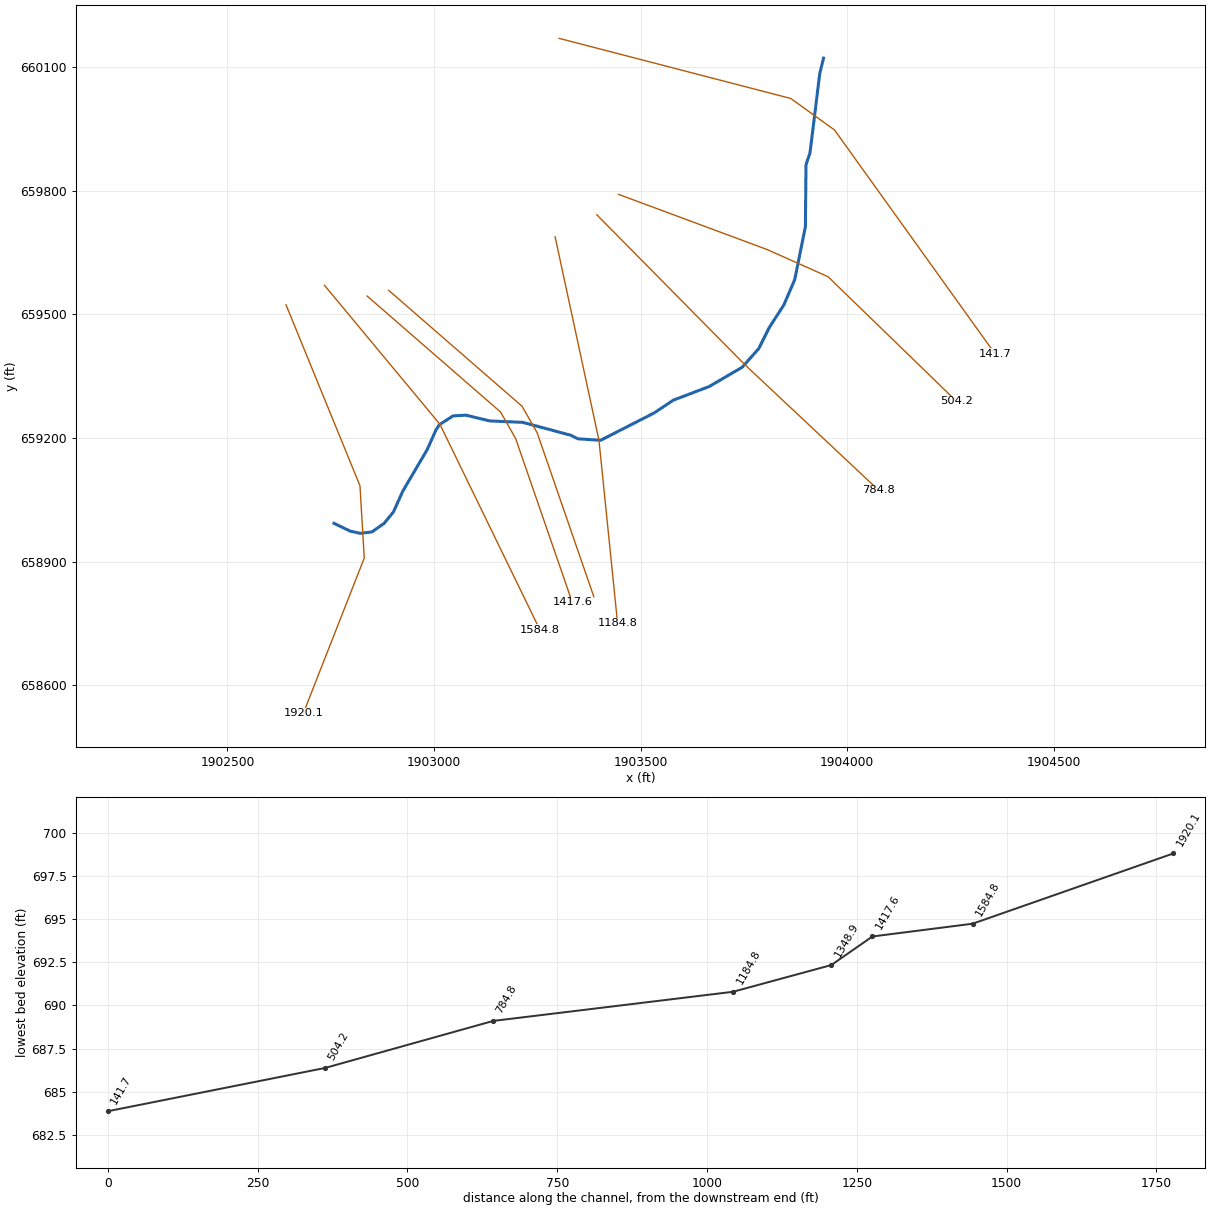
--- PupRun.prj (project) ---

Proj Title=PupRun
Current Plan=p01
Default Exp/Contr=0,0
English Units
Geom File=g01
Flow File=f01
Plan File=p01
BEGIN DESCRIPTION:
AMEC Environment & Infrastructure, 2013
Projection: NAD 1983 State Plane West Virginia South FIPS 4702 (US Feet)
Vertical Datum: NAVD 1988
END DESCRIPTION:
DSS Export Rating Curves= 0
DSS Export Rating Curve Sorted= 0
DSS Export Volume Flow Curves= 0
DXF OffsetX= 0
DXF OffsetY= 0
DXF ScaleX= 0
DXF ScaleY= 0

--- PupRun.p01 (plan) ---

Plan Title=Floodplain
Program Version=4.00
Geom File=g01
Flow File=f01
K Sum by GR=0
Std Step Tol=0.01
Critical Tol=0.01
Num of Std Step Trials=20
Max Error Tol=0.3
Flow Tol Ratio=0.001
Split Flow NTrial=30
Split Flow Tol=0.02
Split Flow Ratio=0.02
Log Output Level=0
Friction Slope Method=1
Unsteady Friction Slope Method=2
Unsteady Bridges Friction Slope Method=1
Global Log Level=0
CheckData=False
Run HTab=0
Run UNet=0
Run PostProcess=0
UNET Theta=0
UNET Theta Warmup=0
UNET ZTol=0
UNET ZSATol=0
UNET MxIter=0
UNET MaxInSteps=0
UNET DtIC=0
UNET DtMin=0
UNET MaxCRTS=0
UNET WFStab=0
UNET SFStab=0
UNET WFX=0
UNET SFX=0
UNET DSS MLevel=0
UNET DZMax Abort=0
UNET Convert EG Bridges=0
UNET Use Existing IB Tables=0
UNET Froude Limit=0
UNET Froude Power=0
Write IC File=0
Echo Input=False
Echo Output=False
Write Detailed=0

--- PupRun.f01 (steady flow) ---

Flow Title=NFF Regression Equation
Program Version=4.10
Number of Profiles= 1
Profile Names=P100yr
River Rch & RM=PupRun,Main            ,1920.1
888.6882
River Rch & RM=PupRun,Main            ,141.7
909.5346
Boundary for River Rch & Prof#=PupRun,Main            , 1
Up Type= 0
Dn Type= 3
Dn Slope=0.00703
DSS Import GetInterval= 0
DSS Import GetPeak= 0
DSS Import FillOption= 0

--- PupRun.g01 (geometry) ---

Geom Title=USGS 3m DEM
Program Version=4.10

River Reach=PupRun          ,Main
Reach XY= 30
     1902757.688       658992.88     1902797.635      658973.777
      1902821.95      658968.568     1902849.738      658972.042
     1902879.262      658992.884     1902901.839      659020.673
     1902924.416      659071.041     1902983.463      659171.775
     1903004.302      659218.669     1903012.982      659232.172
     1903045.984      659253.406     1903077.245      659255.143
     1903134.559      659241.251     1903214.451      659237.781
     1903330.816      659206.523     1903348.184      659197.839
     1903402.997      659194.189     1903532.279       659260.37
     1903579.171      659291.633     1903666.009      659324.634
     1903745.898       659371.53     1903785.843      659416.687
     1903811.893      659468.792     1903846.626      659522.633
     1903872.676      659583.421     1903898.723      659711.943
     1903900.147      659862.515     1903909.829       659891.56
     1903933.446      660083.613     1903942.613      660121.163

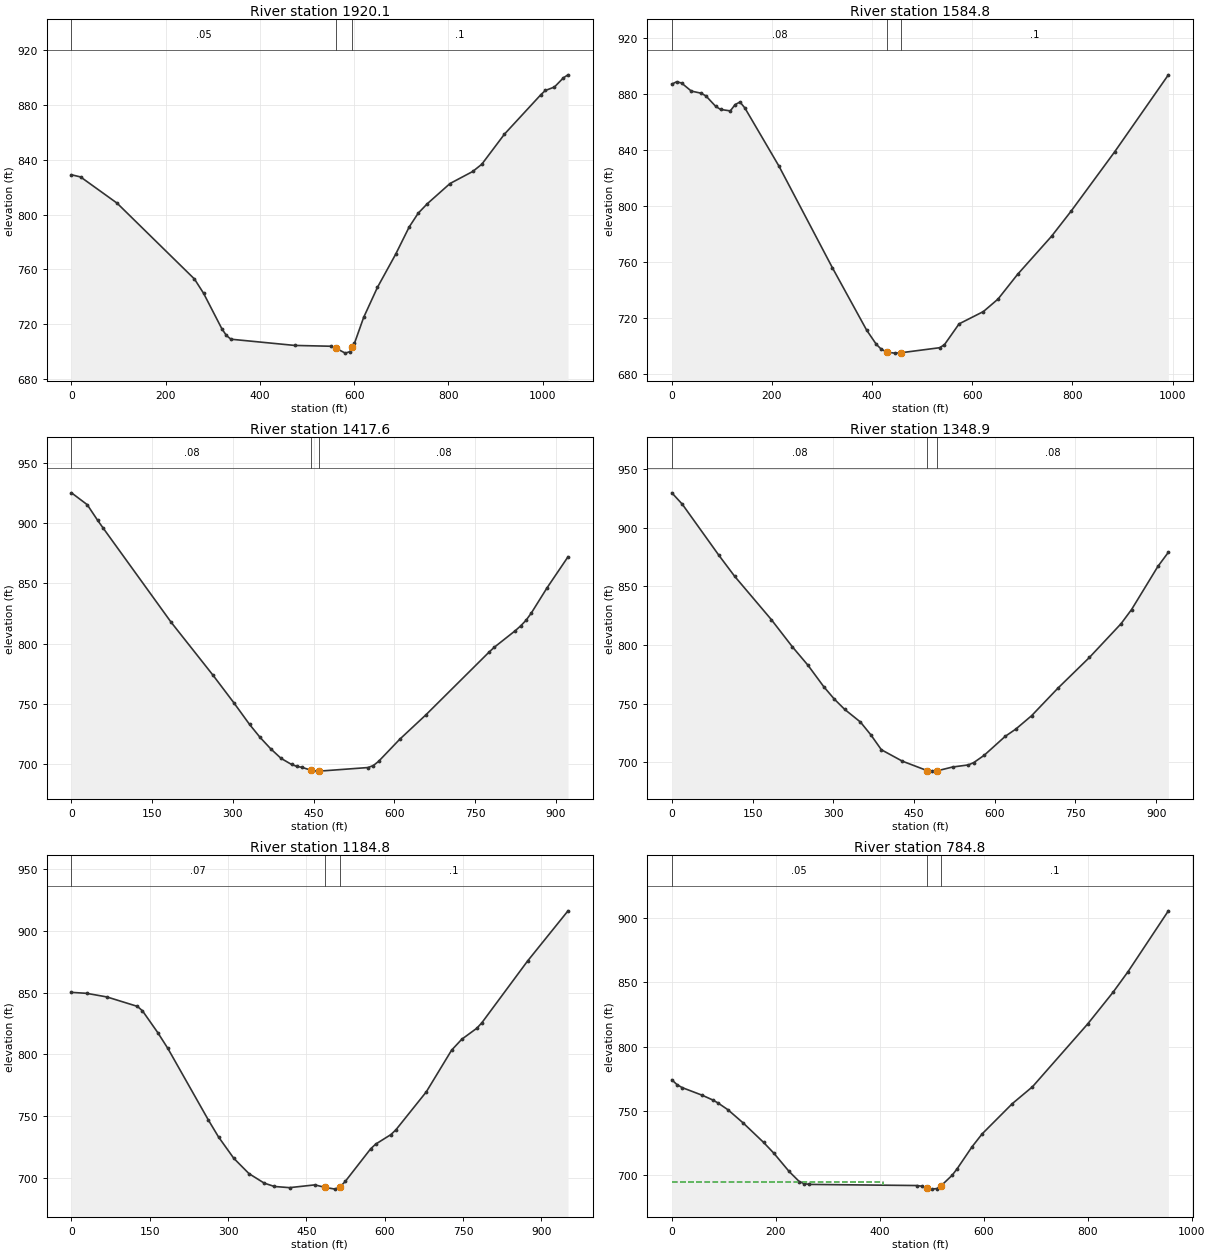
Type RM Length L Ch R = 1 ,1920.1  ,320.7,335.2,341.9
XS GIS Cut Line= 4
     1902641.744      659522.785     1902820.694      659084.026
     1902831.111      658908.679     1902683.542      658531.943
#Sta/Elev= 30
       0     829    19.3  827.42    96.7  808.31   261.1   752.9   280.4  742.51
   319.1  716.69   328.8  711.72   338.5  708.98   473.8  704.44   551.9  703.84
   561.7  702.35   581.2  698.82     591   699.9   596.3   703.2   600.7  705.94
   620.2  724.86   649.5  746.81     688  770.88   716.9   790.9   736.2  801.03
   755.5  807.91   803.6  822.62   851.8  831.41   871.1  836.71   919.2  858.68
   996.3  887.41  1005.9  890.52  1025.2  893.05  1044.5  899.83  1054.1  901.96
#Mann= 3 , 0 , 0
       0     .05       0   561.7    .045       0   596.3      .1       0
Bank Sta=561.7,596.3
XS Rating Curve= 0 ,0
Exp/Cntr=0.3,0.1

Type RM Length L Ch R = 1 ,1584.8  ,170.7,167.2,173.1
XS GIS Cut Line= 3
     1902734.943      659569.972     1903014.166      659233.154
     1903256.069      658734.612
#Sta/Elev= 30
       0  886.85     9.7  888.53    19.4  887.61    38.9  881.85    58.3  880.37
    68.1  878.39    87.5  870.98    97.2  868.76   116.7  867.71   126.4  872.23
   136.1  874.05   145.8  869.82   213.9  828.28   320.8   755.6   388.9  711.23
   408.3  701.03   418.1  697.58     430  695.42     445  694.74     457  694.98
   534.7   698.6   544.4  700.78   573.6  715.63   622.2  724.43   651.4  733.35
   690.3  750.93   758.3   778.2   797.2  796.06   884.7  838.67   991.6  893.47
#Mann= 3 , 0 , 0
       0     .08       0     430    .045       0     457      .1       0
Bank Sta=430,457
XS Rating Curve= 0 ,0
Exp/Cntr=0.3,0.1

Type RM Length L Ch R = 1 ,1417.6  ,62.6,68.7,68.2
XS GIS Cut Line= 4
     1902838.056      659544.096     1903160.972      659262.846
     1903197.431       659198.61     1903334.583       658801.04
#Sta/Elev= 30
       0  925.25    29.2  915.42    48.7  902.32    58.4  896.24   184.9  817.85
   262.8  773.78   301.7  750.79   330.9  732.79   350.4  722.04   369.8  712.72
   389.3  704.64   408.8  699.57   418.5  697.95   428.2  697.18   445.6  694.65
   455.9     694   460.6     694     551  696.98   560.8  698.63   570.6  702.11
   609.7  720.39   658.6   740.8   775.9   792.9   785.7  796.96   824.8  810.77
   834.6  814.68   844.4  819.23   854.2  825.23   883.5  846.22   922.6   872.1
#Mann= 3 , 0 , 0
       0     .08       0   445.6    .045       0   460.6     .08       0
Bank Sta=445.6,460.6
XS Rating Curve= 0 ,0
Exp/Cntr=0.3,0.1

Type RM Length L Ch R = 1 ,1348.9  ,177.3,164.1,152.7
XS GIS Cut Line= 4
     1902890.139      659557.985     1903213.056      659276.735
     1903249.514      659212.499     1903386.667      658814.929
#Sta/Elev= 30
       0  929.72    19.5  919.96    87.6   876.3   116.8  858.47   184.9  821.56
   223.8  798.46     253  782.61   282.2   764.4   301.7  753.87   321.2  744.98
   350.4  734.22   369.8  723.26   389.3  710.58   428.2  700.86   474.4  692.78
   483.6  692.34   492.8  692.58   521.6  695.85     551  697.65   560.8  699.58
   580.3  705.83   619.4     722     639  728.17   668.4  739.59   717.3  763.08
   775.9  789.31   834.6  818.05   854.2  830.17   903.1  866.94   922.6  879.02
#Mann= 3 , 0 , 0
       0     .08       0   474.4    .045       0   492.8     .08       0
Bank Sta=474.4,492.8
XS Rating Curve= 0 ,0
Exp/Cntr=0.3,0.1

Type RM Length L Ch R = 1 ,1184.8  ,386.9,400,415.8
XS GIS Cut Line= 3
      1903292.96      659687.793     1903399.147      659193.914
     1903444.168      658750.187
#Sta/Elev= 30
       0  850.33    29.1  849.55      68  846.61   126.3  838.97     136  835.36
   165.2  817.75   184.6  804.88   262.3  746.76   281.7  733.08   310.9  715.79
     340  703.37   369.2  695.66   388.6  692.94   417.7  691.99   466.3  694.24
   485.7   692.2   505.2  690.79   514.9  692.79   524.6  697.11     573  723.42
   582.7  727.28   611.8  734.99   621.5  738.89   679.7  769.66   728.2  803.48
   747.6   812.3   776.6  821.28   786.3  825.77   873.6  875.69   951.2  916.45
#Mann= 3 , 0 , 0
       0     .07       0   485.7    .045       0   514.9      .1       0
Bank Sta=485.7,514.9
XS Rating Curve= 0 ,0
Exp/Cntr=0.3,0.1

Type RM Length L Ch R = 1 ,784.8   ,272.5,280.7,288.4
XS GIS Cut Line= 3
     1903393.785      659741.273     1903751.696      659378.085
      1904076.04      659073.001
#Sta/Elev= 30
       0  774.15     9.8  770.45    19.6  768.12    58.8  762.08    78.4  758.52
    88.2  756.28   107.9  750.87   137.3  740.54   176.5  725.44   196.1   717.1
   225.5  702.88   245.2  694.96     255  693.32   264.8  692.78   470.7   691.9
   480.5   691.4   490.3  690.17   500.1   689.1   509.9  689.55   517.4   691.5
     539   699.8   548.6  704.81   577.7  722.16     597  732.11   655.1  755.66
   693.8  768.76   800.3  817.77   848.7  842.24   877.8  858.41   955.2  905.62
#Mann= 3 , 0 , 0
       0     .05       0   490.3    .045       0   517.4      .1       0
#XS Ineff= 2 , 0
          406.77   694.9
Permanent Ineff=
       F       F
Bank Sta=490.3,517.4
XS Rating Curve= 0 ,0
Exp/Cntr=0.3,0.1

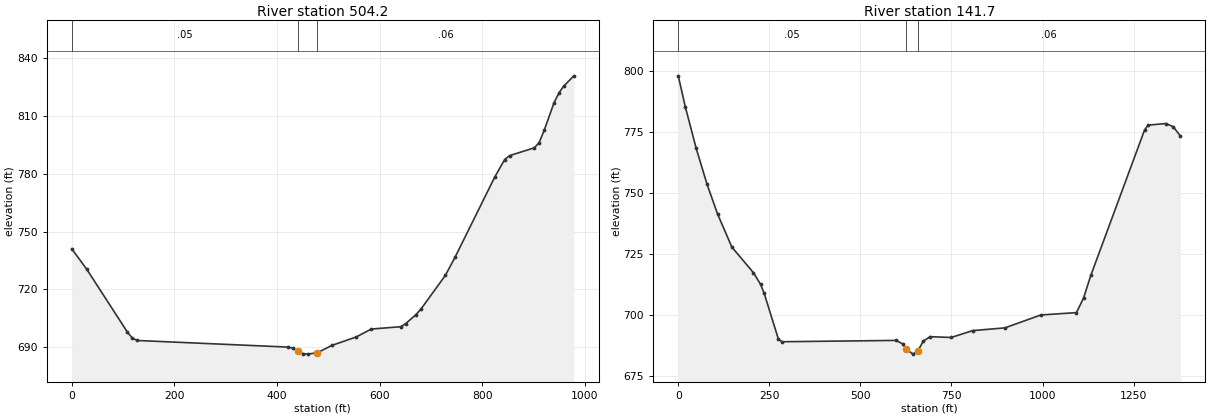
Type RM Length L Ch R = 1 ,504.2   ,367.5,362.5,357
XS GIS Cut Line= 4
     1903446.562      659790.624     1903805.937      659656.943
     1903953.507      659590.971     1904264.271      659288.887
#Sta/Elev= 30
       0  741.08    29.5  730.33   108.2  697.89     118  694.67   127.8  693.46
   421.5  690.02     431  689.46   440.5  687.81     450   686.6   459.5  686.37
   478.5  687.06     507  690.91   554.7  695.32   583.6  699.39   641.4  700.62
     651  702.27   670.3  706.76   679.9  709.55   728.1  727.26   747.3  736.87
   824.4  778.37   843.6   787.4   853.3  789.47   901.4   793.5     911  796.28
   920.7  802.62     940  816.99   949.6  822.09   959.2  825.69   978.5  830.91
#Mann= 3 , 0 , 0
       0     .05       0   440.5    .045       0   478.5     .06       0
Bank Sta=440.5,478.5
XS Rating Curve= 0 ,0
Exp/Cntr=0.3,0.1

Type RM Length L Ch R = 1 ,141.7   ,132.2,141.7,151.1
XS GIS Cut Line= 4
     1903302.465      660169.096     1903863.229      660023.262
     1903969.132      659946.874     1904358.021      659403.471
#Sta/Elev= 30
       0  798.04    19.6  785.24    49.1  768.39    78.6  753.77     108  741.34
   147.3  727.75   206.2  717.32   225.9  712.53   235.7  708.91     275  690.01
   284.8  688.94   598.1  689.49   616.7  688.02     626  685.86   644.7  683.86
   658.3  685.32   672.7   689.2   691.3  691.02   749.3  690.69   808.3  693.51
   896.7  694.63     995  699.91  1093.2   700.9  1112.9     707  1132.6  716.19
    1280   775.8  1289.8  777.82  1338.9  778.47  1358.6  777.18  1378.2  773.39
#Mann= 3 , 0 , 0
       0     .05       0     626    .045       0   658.3     .06       0
Bank Sta=626,658.3
XS Rating Curve= 0 ,0
Exp/Cntr=0.3,0.1

Chan Stop Cuts=-1
Use User Specified Reach Order=0
Composite Channel Slope=5